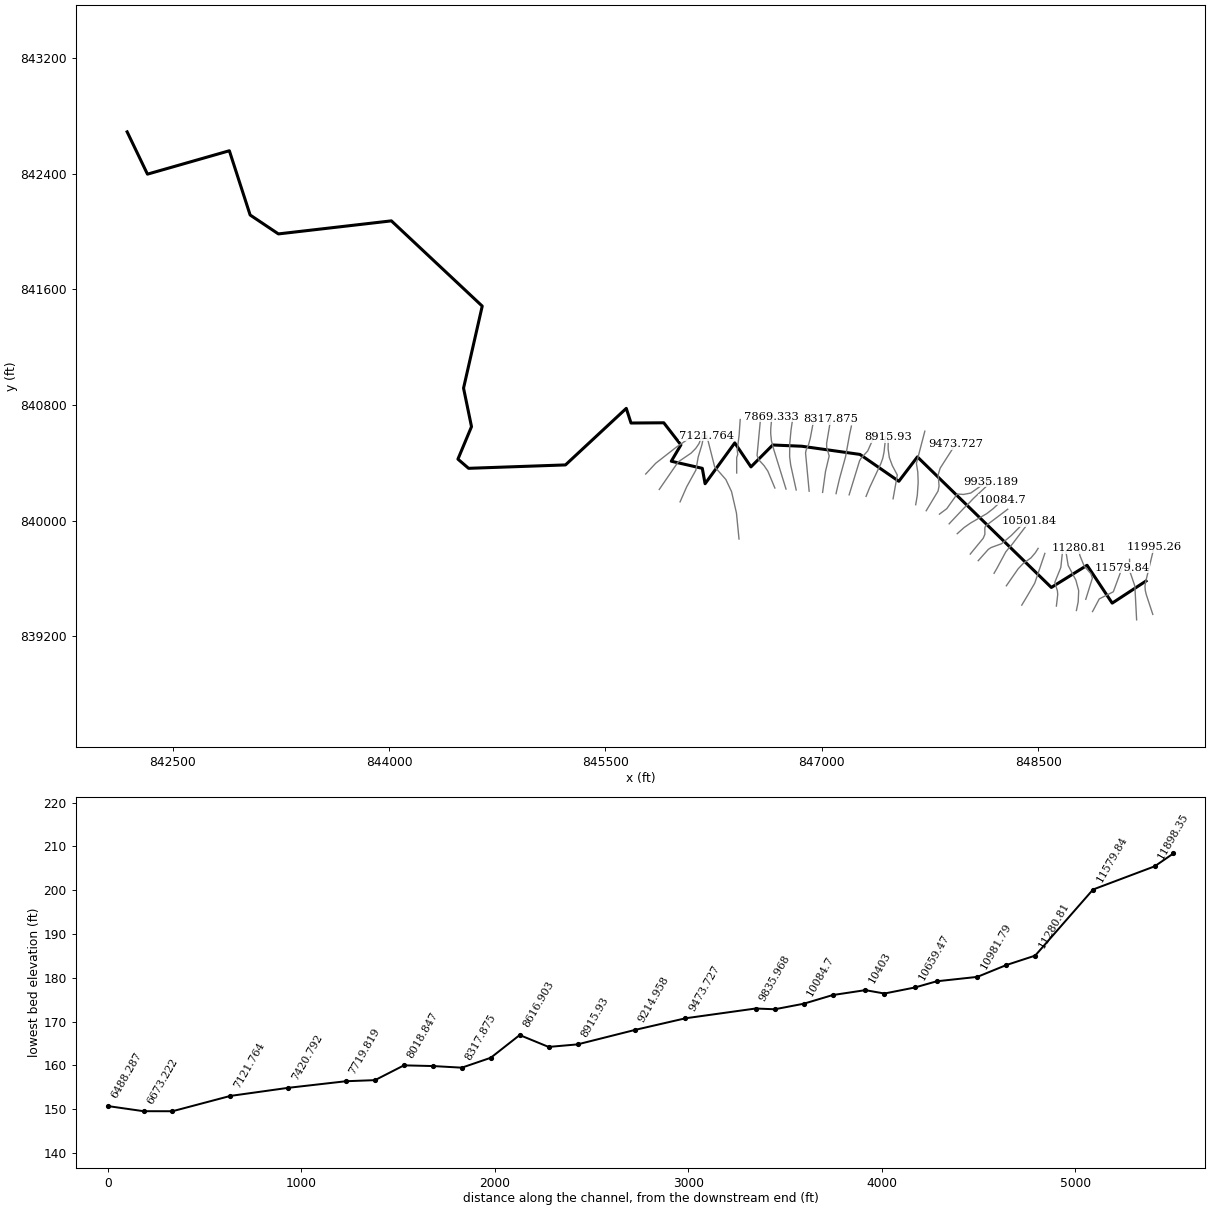
--- 18599_ras.prj (project) ---

Proj Title=18599
Current Plan=p01
Default Exp/Contr=0.3,0.1
English Units
Geom File=g01
Flow File=f01
Plan File=p01
Y Axis Title=Elevation
X Axis Title(PF)=Main Channel Distance
X Axis Title(XS)=Station
BEGIN DESCRIPTION:
RFD model 18599 exported to HEC-RAS
END DESCRIPTION:

--- 18599_ras.p01 (plan) ---

Plan Title=Plan 01
Program Version=4.10
Short Identifier=Plan 01
Geom File=g01
Flow File=f01
Subcritical Flow
Calc Critical at every XS
Secant Critical Depth

--- 18599_ras.f01 (steady flow) ---

Flow Title=Flow 01
Program Version=5.01
Number of Profiles= 6
Profile Names=10yr,25yr,50yr,100yr,100plus,500yr
River Rch & RM=18599,40,11995.26
  317.75  460.48     583  679.18   991.6 1422.11
River Rch & RM=18599,40,11898.35
  318.84  462.07  585.04  681.58   995.1 1426.51
River Rch & RM=18599,40,11579.84
  332.23   481.6   609.9  710.62  1037.5 1478.88
River Rch & RM=18599,40,11280.81
  349.34  506.78  642.12  748.47 1092.77  1547.6
River Rch & RM=18599,40, 11131.3
  364.64   528.9  670.11     781 1140.26 1604.67
River Rch & RM=18599,40,10981.79
  398.59  577.84  731.92  852.71 1244.95 1728.73
River Rch & RM=18599,40,10771.54
   410.9     596   755.2  880.09 1284.92 1777.38
River Rch & RM=18599,40,10659.47
  412.44  598.26   758.1   883.5 1289.91 1783.42
River Rch & RM=18599,40,10501.84
  435.64  633.16  803.39  937.35 1368.53 1881.04
River Rch & RM=18599,40,   10403
  470.19  684.32  869.16 1014.86 1481.69 2017.15
River Rch & RM=18599,40,10234.22
  471.07  685.67  870.91 1016.97 1484.77 2020.99
River Rch & RM=18599,40, 10084.7
  477.33  695.18  883.33  1031.8 1506.43 2047.75
River Rch & RM=18599,40,9935.189
  478.21  696.51  885.08  1033.9  1509.5 2051.57
River Rch & RM=18599,40,9835.968
  505.55   737.9  939.02 1098.26 1603.45 2166.55
River Rch & RM=18599,40,9473.727
  507.72  741.21  943.35 1103.44 1611.02 2175.87
River Rch & RM=18599,40,9214.958
     590  866.81 1107.93 1300.75 1899.09 2526.37
River Rch & RM=18599,40, 8915.93
   596.7  877.02 1121.31 1316.76 1922.47  2554.4
River Rch & RM=18599,40,8766.416
  599.63  881.48 1127.15 1323.76 1932.69 2566.63
River Rch & RM=18599,40,8616.903
  600.88  883.39 1129.65 1326.75 1937.06 2571.86
River Rch & RM=18599,40,8467.389
  629.86  927.77 1187.93 1396.76 2039.27 2694.53
River Rch & RM=18599,40,8317.875
  642.65  947.26 1213.44 1427.31 2083.88  2747.4
River Rch & RM=18599,40,8168.361
  643.87  949.13 1215.89 1430.25 2088.16  2752.5
River Rch & RM=18599,40,8018.847
  669.08  987.43 1265.96 1490.14 2175.61 2855.32
River Rch & RM=18599,40,7869.333
  695.66 1028.71 1320.66 1556.34 2272.26 2971.54
River Rch & RM=18599,40,7719.819
  697.59 1031.69 1324.59 1561.09 2279.19 2979.78
River Rch & RM=18599,40,7121.764
   707.4 1046.92 1344.77  1585.5 2314.83 3022.45
River Rch & RM=18599,40,6822.736
  727.02 1077.16 1384.66 1633.61 2385.07 3105.47
River Rch & RM=18599,40,6673.222
   729.7  1081.3 1390.12 1640.19 2394.68 3116.79
River Rch & RM=18599,40,6488.287
  727.02 1077.16 1384.66 1633.61 2385.07 3105.47
River Rch & RM=18599,40,6356.994
  731.62 1084.25 1394.02 1644.89 2401.54 3124.88
River Rch & RM=18599,40,6075.167
  746.79 1107.86 1425.34 1682.84 2456.95 3190.83
River Rch & RM=18599,40, 5830.43
   750.8 1114.12 1433.66 1692.94  2471.7 3208.44
River Rch & RM=18599,40,5626.625
  753.01 1117.56 1438.23 1698.48 2479.78 3218.02
River Rch & RM=18599,40,5477.111
   757.5 1124.51 1447.42 1709.59    2496 3237.16
River Rch & RM=18599,40,5151.294
  759.34 1127.37 1451.22 1714.19 2502.72 3245.12
Boundary for River Rch & Prof#=18599,40,1
Up Type= 0
Dn Type= 2
Boundary for River Rch & Prof#=18599,40,2
Up Type= 0
Dn Type= 2
Boundary for River Rch & Prof#=18599,40,2
Up Type= 0
Dn Type= 2
Boundary for River Rch & Prof#=18599,40,2
Up Type= 0
Dn Type= 2
Boundary for River Rch & Prof#=18599,40,2
Up Type= 0
Dn Type= 2
Boundary for River Rch & Prof#=18599,40,2
Up Type= 0
Dn Type= 2

--- 18599_ras.g01 (geometry) ---

Geom Title=18599
Program Version=4.10

River Reach=18599,40
Reach XY= 30
849247.736725926839582.679825768 849013.04260999839429.412240848
848838.705612659839691.341061026848591.050387472 839537.83258839
847662.494920313840441.235827968847533.750788629840272.393887088
847264.179338038840458.329658926846861.617498308840514.869553551
846659.478224903840523.510857835846508.527960628840372.023404017
846396.335727811840537.980163723846190.511745512840255.453271121
846171.200722784840362.103713825 845956.24895519840411.205513731
846022.905735403840524.027777493845904.189714015840677.147069871
845676.958533287840675.535501212845644.128949285840777.014481708
845222.635359198840385.683200985844550.931253105840362.114434063
 844476.92690894840425.638002053844571.103408188840650.443051219
844515.911476195840916.863089606844645.466761231841484.500186726
844015.604585558842074.249034107843232.276936859841983.960730731
843036.347017735842114.785578623842892.268947452842559.342128798
842324.487504184842397.431010872842183.597409159 842690.02256386

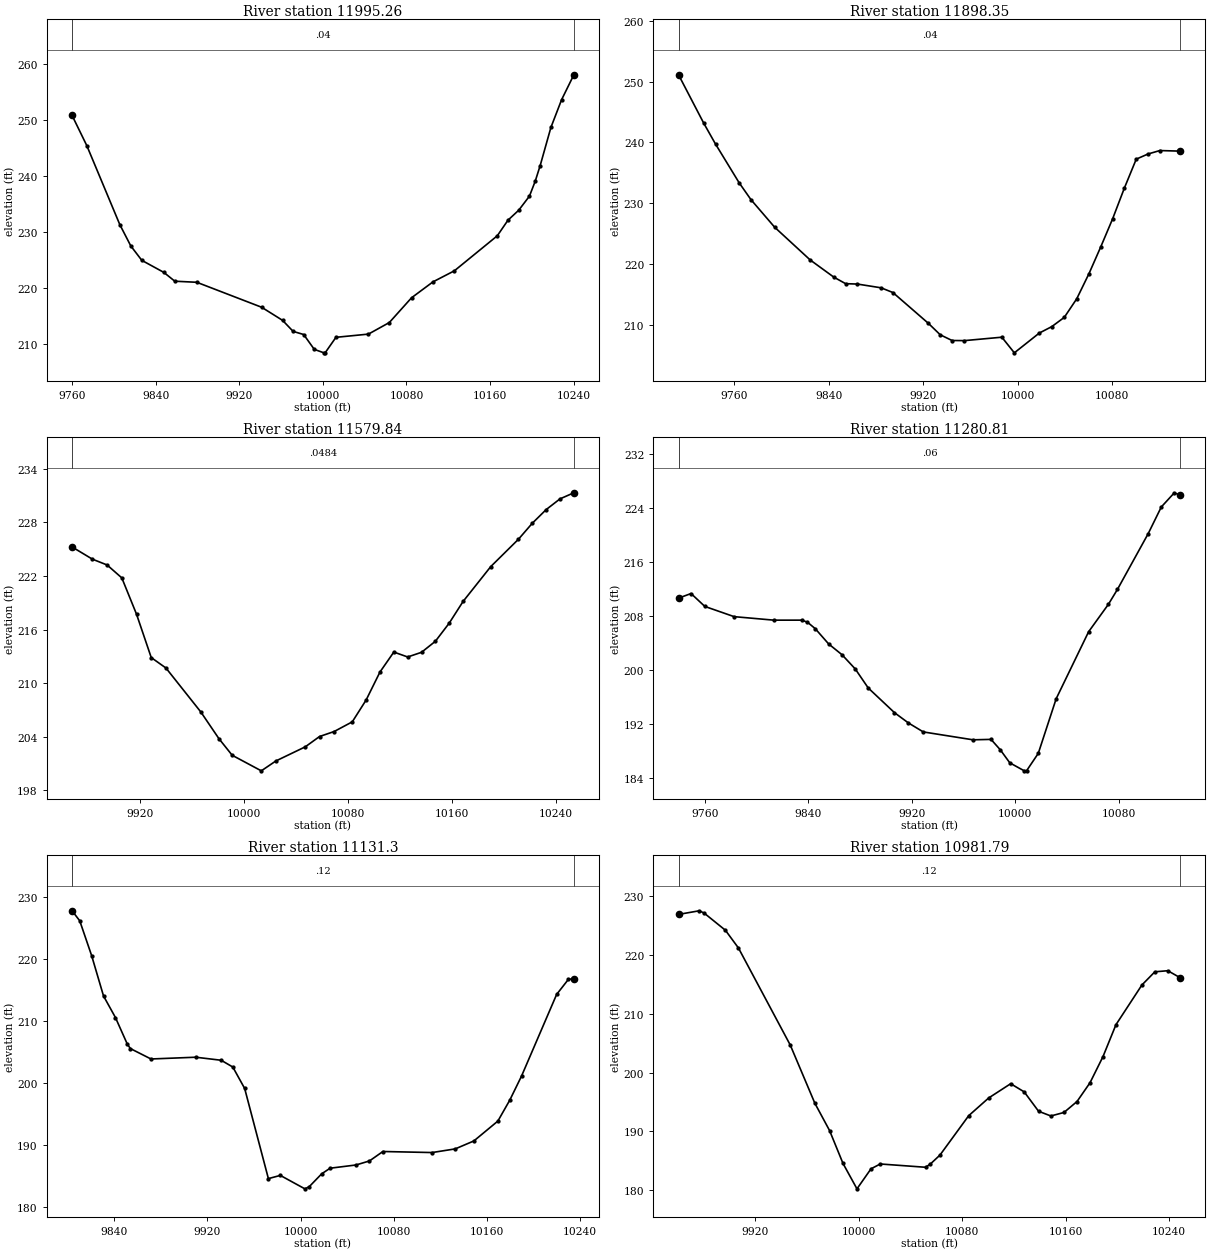
Type RM Length L Ch R = 1 ,11995.26,96.906700,96.906700,96.906700
XS GIS Cut Line= 6
849294.497772884839351.603814066849249.351222506839488.392494171
849242.428604725839517.496978545849240.317852851839545.797398617
849243.979491657839572.644317908849303.331604393839816.423679531
#Sta/Elev= 30
9759.862250.88379773.969245.47999805.561231.35279816.092227.53559826.622224.9588
9847.683 222.8099858.214221.22729879.275221.03559941.349216.56939961.405214.2222
9971.492212.25119981.585211.69259991.738209.0352   10001208.415410002.11208.4154
10012.48211.190810043.57211.765510063.59213.836710084.82218.258410105.35 221.108
10125.88223.091810166.93229.3496 10177.2  232.1510187.46233.925510197.72236.4442
10203.26239.117810207.99241.909210218.25248.722310228.52253.699410240.24 258.152
#Mann= 3 , 0 , 0
9759.862    0.04       09759.862    0.04       010240.24    0.04       0
#XS Ineff= 2 , 0
       0                               0
Bank Sta=9759.862,10240.24
Exp/Cntr=0.3,0.1

Type RM Length L Ch R = 1 ,11898.35,318.511200,318.511200,318.511200
XS GIS Cut Line= 4
849182.344283074839313.737214193849170.186945558839547.524220154
849134.721815944839651.031189844849133.320312828839732.318367988
#Sta/Elev= 30
9712.986251.10749734.278243.17699744.291239.73799764.318233.37359774.332230.6063
9794.359226.08749824.399220.72099844.426217.8971 9854.44216.82169864.453216.7585
 9884.48216.14229894.494215.36559924.534210.30779934.548208.43179944.561207.4945
9954.991207.47499986.704208.03669997.274205.469910018.42208.718210028.99209.7754
10039.56211.290910050.13214.350910060.47218.469210070.47222.874910080.48 227.464
10090.48232.538510100.48237.260810110.48 238.10810120.48238.6718 10137.8238.5754
#Mann= 3 , 0 , 0
9712.986    0.04       09712.986    0.04       0 10137.8    0.04       0
#XS Ineff= 2 , 0
       0                               0
Bank Sta=9712.986,10137.8
Exp/Cntr=0.3,0.1

Type RM Length L Ch R = 1 ,11579.84,299.027800,299.027800,299.027800
XS GIS Cut Line= 4
848876.816613585839371.198840097848923.457755089 839458.71878393
849020.748562604839507.887256518849082.614049464839675.004415825
#Sta/Elev= 30
9867.399225.24819883.037223.88129894.369223.2288  9905.7 221.7839917.031217.7152
9928.363212.85689939.694211.68619966.571 206.7599980.497203.76989990.708201.9127
10013.12200.169710024.32 201.27510047.01202.861410057.93204.013110069.18204.5725
10083.16205.657610093.83208.104610104.49211.239810115.15213.472910125.82212.9242
10136.48213.446710147.14214.681110157.81216.714910168.47219.1413 10189.8 223.049
10211.12226.111710221.79227.904310232.45229.431310243.11230.633610253.78231.3159
#Mann= 3 , 0 , 0
9867.399  0.0484       09867.399  0.0484       010253.78  0.0484       0
#XS Ineff= 2 , 0
       0                               0
Bank Sta=9867.399,10253.78
Exp/Cntr=0.3,0.1

Type RM Length L Ch R = 1 ,11280.81,149.513900,149.513900,149.513900
XS GIS Cut Line= 6
848829.833623493839455.956685585 848875.78492315839602.679108267
848864.925814468839633.714613898848818.532566576  839686.0835555
848788.151870696839761.624576973848780.566588891839809.620085602
#Sta/Elev= 30
 9739.65210.61759749.315211.29979760.002209.39259782.646207.88129813.437 207.362
 9834.81207.36469839.345 207.0659845.402206.09959855.746203.84379866.091 202.248
9876.324200.14649886.366197.33039906.661193.68029917.398192.16469928.951190.8309
9967.365 189.6669981.337189.72819988.494188.18789995.847186.260910006.76185.1088
10008.78185.076310017.87187.659410031.71195.7408 10056.8 205.64810072.13 209.713
10079.09211.910310102.93220.175910113.02 224.10310123.09226.202310127.73225.8338
#Mann= 3 , 0 , 0
 9739.65    0.06       0 9739.65    0.06       010127.73    0.06       0
#XS Ineff= 2 , 0
       0                               0
Bank Sta=9739.65,10127.73
Exp/Cntr=0.3,0.1

Type RM Length L Ch R = 1 , 11131.3,149.513900,149.513900,149.513900
XS GIS Cut Line= 6
848764.911197762 839378.55255839848777.241862282839438.527835435
848780.699137194839515.230224989848761.169829413839588.489941332
848707.868090774839689.759180473848691.496248962839789.759807111
#Sta/Elev= 30
9803.953 227.8229810.535226.20289820.744220.58089830.953214.05739841.162210.5857
9851.372206.2807 9854.05 205.5629871.688203.88599910.092204.17149931.898203.6809
9941.903202.58529952.076199.1234 9972.43184.56569982.672185.082910003.75 182.914
10007.42183.250610018.19185.342910025.39186.244810047.62186.768110059.17187.4201
10070.72188.9444 10112.9 188.77510132.77189.365410148.76190.647710169.37193.8591
10179.59197.239510189.66201.1185 10219.8214.313210229.81216.728610234.58216.8712
#Mann= 3 , 0 , 0
9803.953    0.12       09803.953    0.12       010234.58    0.12       0
#XS Ineff= 2 , 0
       0                10073.65       0
Bank Sta=9803.953,10234.58
Exp/Cntr=0.3,0.1

Type RM Length L Ch R = 1 ,10981.79,210.250000,210.250000,210.250000
XS GIS Cut Line= 6
848626.109827679 839409.24339331848635.367045347 839488.80974183
848633.203774779839513.989530687848615.255732506839573.517215025
848656.678759737839675.609568969848668.456128523839784.622482961
#Sta/Elev= 30
9860.484226.94879876.553227.56629880.334227.16899896.767224.24819906.853221.2295
9946.948204.70549966.007194.78459977.371190.14659987.762184.54799998.579180.2181
10009.45183.629110016.61184.450910051.64183.891710055.32184.429110062.79  185.96
10085.09192.6827 10100.5195.688110117.55198.120310128.02196.726510139.12193.4318
10148.63192.626210158.76193.219610168.89195.088910178.96198.2881   10189202.7411
10199.03208.171210219.11214.929310229.14217.176810239.18217.358710248.84216.1495
#Mann= 3 , 0 , 0
9860.484    0.12       09860.484    0.12       010248.84    0.12       0
#XS Ineff= 2 , 0
       0                               0
Bank Sta=9860.484,10248.84
Exp/Cntr=0.3,0.1

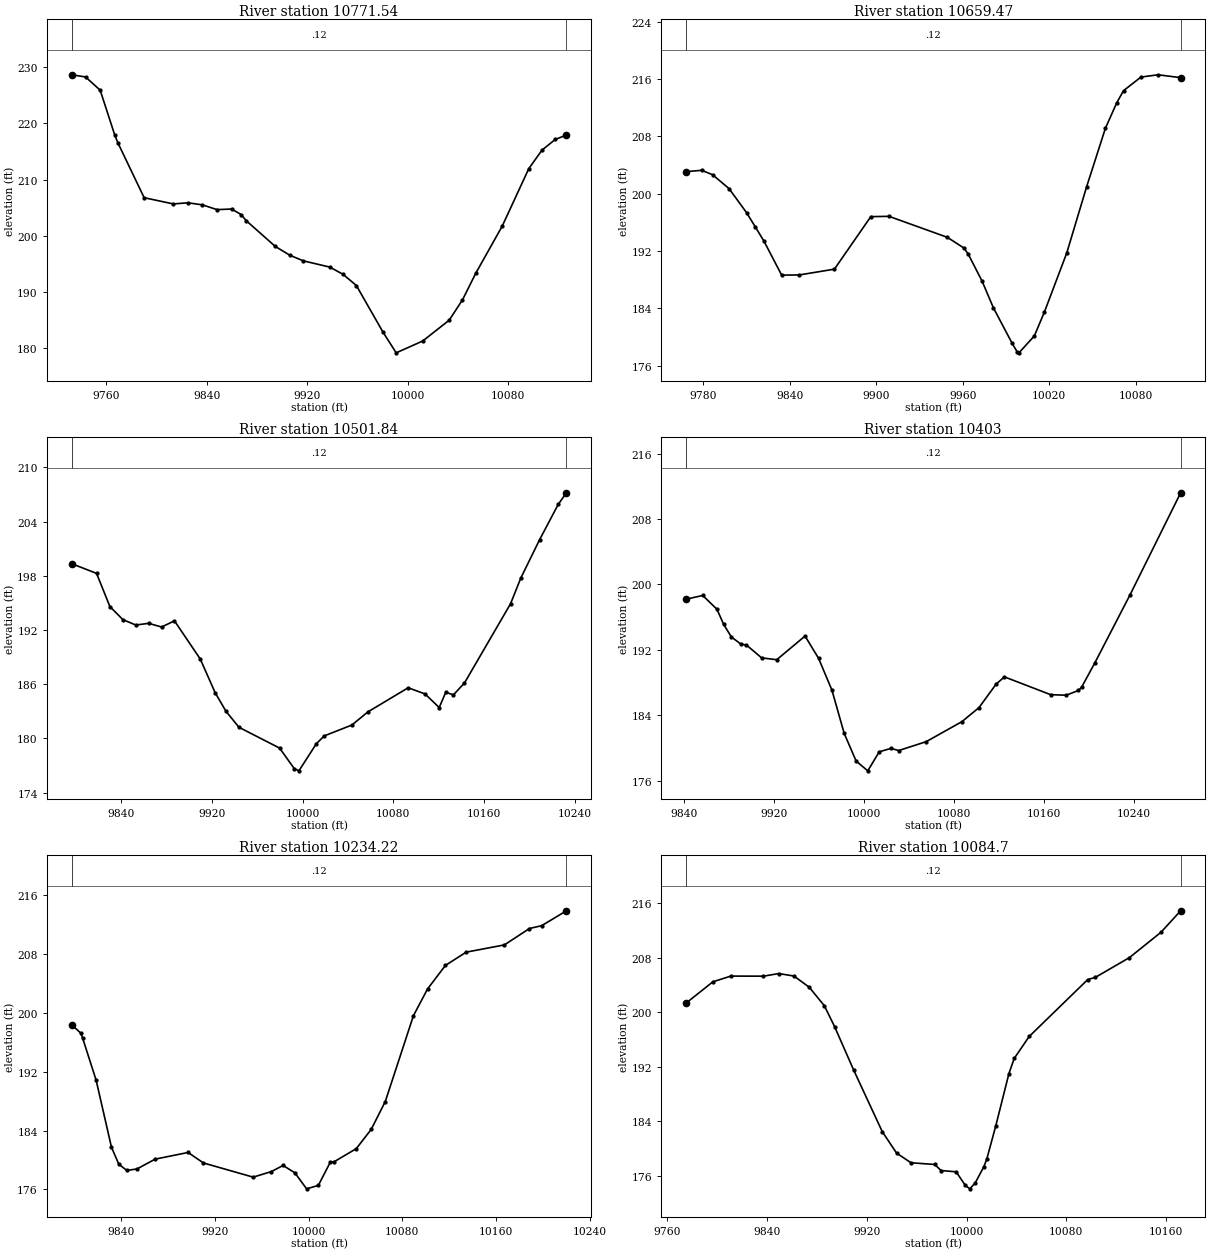
Type RM Length L Ch R = 1 ,10771.54,112.065900,112.065900,112.065900
XS GIS Cut Line= 4
848386.072272414839415.586603737 848421.47331159839474.357128223
848475.986735225839567.409270063848546.061888754839773.430221543
#Sta/Elev= 30
9732.438228.63179743.428228.24589755.102225.89189766.776217.87929769.121 216.577
9790.124206.78349813.382205.67669824.972205.87859836.562205.51019848.151204.6639
9859.741204.77179867.374203.78969871.331202.7177 9894.51198.1346  9906.1196.5634
 9916.91195.55999938.035 194.4479948.598 193.156 9959.16191.17359980.286182.9159
9990.848179.210810011.97181.3104 10033.1185.017710043.66188.624110054.22 193.349
10075.35201.751610096.47211.950810107.04215.2556 10117.6 217.147 10126.5217.9205
#Mann= 3 , 0 , 0
9732.438    0.12       09732.438    0.12       0 10126.5    0.12       0
#XS Ineff= 2 , 0
       0                               0
Bank Sta=9732.438,10126.5
Exp/Cntr=0.3,0.1

Type RM Length L Ch R = 1 ,10659.47,157.630500,157.630500,157.630500
XS GIS Cut Line= 6
848279.209123086 839549.32111107848361.191285656839667.193483704
848397.156950143839705.000740112848450.744812188 839743.25215805
848480.095087644839777.879998967848499.481122763839808.205169878
#Sta/Elev= 30
9767.964 203.0649778.927203.2508 9786.43202.63949797.858200.70989810.026197.3532
9816.187195.34029822.208 193.3449834.389188.63679846.571188.6599    9871189.4691
9896.252196.79179908.878196.83349949.357193.90619960.908192.40879963.881191.5499
9973.465187.79369981.284184.08229994.296179.13229997.782177.9349 9999.01177.7993
10009.71180.155710016.64183.467210032.19191.724410046.03200.991310059.01209.1164
10066.86212.661210071.61214.363710083.69 216.25410095.55216.573110111.23216.1722
#Mann= 3 , 0 , 0
9767.964    0.12       09767.964    0.12       010111.23    0.12       0
#XS Ineff= 2 , 0
       0                               0
Bank Sta=9767.964,10111.23
Exp/Cntr=0.3,0.1

Type RM Length L Ch R = 1 ,10501.84,98.838800,98.838800,98.838800
XS GIS Cut Line= 6
848193.958669237839635.993811561848213.126377447839668.788081964
848274.990483655839783.691395779848292.365292028839805.188004448
848320.140129759839837.355218052848439.336664356839994.223152395
#Sta/Elev= 30
9796.795199.33699818.676198.26799830.393 194.5969841.835193.15139853.193192.5519
 9864.55192.74069875.907192.33359887.264193.01549909.979188.7914 9923.11185.0582
9932.693182.99899944.051181.2392 9979.82 178.9379992.678176.67719996.846176.4197
10012.19179.419910019.13180.283910043.45181.486810057.58 182.94110093.04185.6101
10107.82184.931810120.38183.4235 10126.1185.101710132.94184.833910142.63186.1429
10183.18194.906810192.21197.752110208.74201.985410225.27205.925210232.44207.1844
#Mann= 3 , 0 , 0
9796.795    0.12       09796.795    0.12       010232.44    0.12       0
#XS Ineff= 2 , 0
       0                10033.57       0
Bank Sta=9796.795,10232.44
Exp/Cntr=0.3,0.1

Type RM Length L Ch R = 1 ,   10403,168.784200,168.784200,168.784200
XS GIS Cut Line= 6
848084.403169752839723.235171954848153.542752939 839800.74171325
848173.008562549839813.908023325848246.148411995839840.457447944
 848313.53716858839897.421519307848415.928850615840000.323115409
#Sta/Elev= 30
9841.907198.17929856.829198.64119869.513196.95489875.388195.12179882.297193.5619
9890.768192.6931 9895.73192.57539909.164191.00719922.619190.78529947.738193.6772
 9959.81190.93339971.638187.05049982.479181.77889993.106178.385810003.44177.1894
10013.62179.5171   10024179.934410030.98179.673810055.33180.758810087.04183.2054
10102.18 184.91610117.33 187.77710124.77188.6846 10165.8186.509810179.61186.4374
 10190.6187.024410193.43 187.43610204.99190.359910236.17198.660110281.36211.2034
#Mann= 3 , 0 , 0
9841.907    0.12       09841.907    0.12       010281.36    0.12       0
#XS Ineff= 2 , 0
       0                10085.01       0
Bank Sta=9841.907,10281.36
Exp/Cntr=0.3,0.1

Type RM Length L Ch R = 1 ,10234.22,149.513900,149.513900,149.513900
XS GIS Cut Line= 6
848029.013220848839769.051549426848118.933125671839878.424540748
848130.271490462839905.933951138848130.056382199839950.649372115
848135.751047927839964.025643673848288.710285365840079.076712453
#Sta/Elev= 30
9797.536198.38989805.325197.24459806.812196.60499818.417190.8351 9831.51181.7167
9837.797179.41069844.602178.5677 9853.29178.77179868.782180.10359896.973181.0142
9910.066179.58539952.561177.65489968.089178.41249978.163179.24729988.196178.2397
9998.222176.064110008.24176.531210018.39179.668110021.74179.748710040.68181.5391
10053.39184.148610065.44187.949210089.53199.645310101.58203.274210116.84 206.473
10134.56208.276110167.18209.260210188.63211.494210199.05211.879510220.26213.9067
#Mann= 3 , 0 , 0
9797.536    0.12       09797.536    0.12       010220.26    0.12       0
#XS Ineff= 2 , 0
       09934.053                       0
Bank Sta=9797.536,10220.26
Exp/Cntr=0.3,0.1

Type RM Length L Ch R = 1 , 10084.7,149.513900,149.513900,149.513900
XS GIS Cut Line= 6
847938.705558403839909.885607774847986.798670553839952.859301213
848031.878066499839984.092767297848143.383712986840048.624906521
848186.684578938840082.145331758848255.122394992840145.772666224
#Sta/Elev= 30
9774.945201.30959796.578204.45469810.953205.29329837.127205.28229849.458205.6655
9861.624205.2981 9873.79203.66689885.955200.95289894.323197.82389909.419191.5343
9932.427182.46869943.932179.3206 9955.48177.91369974.465177.66069979.598176.7725
9991.658176.5861    9999174.594310002.63174.088510006.96174.961310013.84177.3213
10016.21178.4459 10023.5183.375610033.91190.955210038.19193.206810050.25 196.442
10097.14204.779910103.27205.106110130.57208.000210155.88211.7162 10171.7214.8732
#Mann= 3 , 0 , 0
9774.945    0.12       09774.945    0.12       0 10171.7    0.12       0
#XS Ineff= 2 , 0
       0                               0
Bank Sta=9774.945,10171.7
Exp/Cntr=0.3,0.1

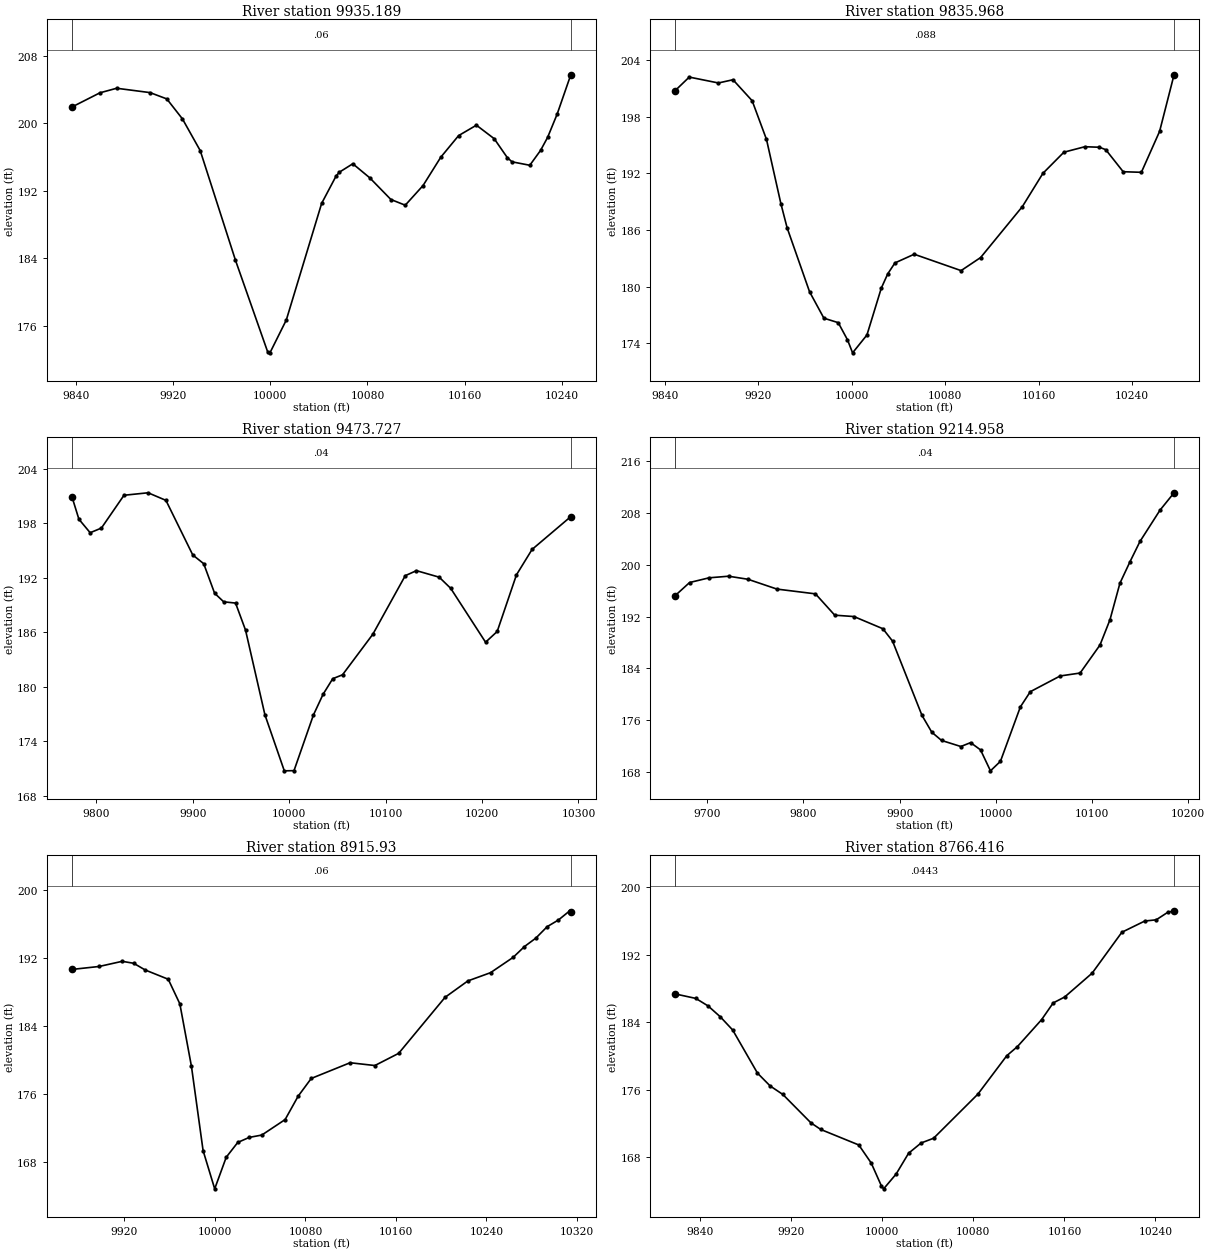
Type RM Length L Ch R = 1 ,9935.189,99.221700,99.221700,99.221700
XS GIS Cut Line= 6
847882.650981806839978.098923744847887.972893951839984.023577269
847987.347226943 840089.15353728848005.499795108  840105.6756566
848050.571732012840153.446292615848173.216229186840268.047798481
#Sta/Elev= 30
9836.678 201.9219859.746203.60289873.507204.14139901.028203.62589914.788202.8806
9927.659200.51599942.309196.75939971.331183.78159997.896172.91169999.707 172.824
10013.18 176.71310042.27190.515210054.17193.754510056.84194.206110067.92195.2035
10081.81193.548410099.28190.9731 10111.1190.298510125.75192.625810140.34 195.978
10155.04198.537910169.69199.769510184.34198.169710195.08195.938810198.98195.4339
10213.63195.025510222.46196.775310228.28198.318910236.14 201.07310247.39205.7368
#Mann= 3 , 0 , 0
9836.678    0.06       09836.678    0.06       010247.39    0.06       0
#XS Ineff= 2 , 0
       0                               0
Bank Sta=9836.678,10247.39
Exp/Cntr=0.3,0.1

Type RM Length L Ch R = 1 ,9835.968,362.240600,362.240600,362.240600
XS GIS Cut Line= 6
847815.355514885840045.096444911847866.332899272840083.162400261
847938.585066379840184.529767675847982.180367599840181.346431075
848032.501161728  840191.1777874848149.362033714 840273.45728682
#Sta/Elev= 30
9848.996200.77329861.033202.20519885.993 201.5819898.474201.92379914.874199.7004
9927.154195.60069939.435188.81429944.779186.24779963.995179.46899976.275176.6668
9988.556176.19129996.465174.376910000.84172.995310013.12174.8866 10025.4179.8477
10030.92181.3605 10037.1182.521310053.58183.440810093.69181.704910110.41183.0901
10146.19188.494510163.76192.013510181.69194.247710199.63194.8288 10212.1 194.773
10217.52194.515310232.43192.181110248.01192.118210263.59 196.45110275.97202.4494
#Mann= 3 , 0 , 0
9848.996   0.088       09848.996   0.088       010275.97   0.088       0
#XS Ineff= 2 , 0
       0                               0
Bank Sta=9848.996,10275.97
Exp/Cntr=0.3,0.1

Type RM Length L Ch R = 1 ,9473.727,258.768800,258.768800,258.768800
XS GIS Cut Line= 6
847723.579148116840068.784735475847805.823143997840204.928709113
847812.669259888840238.982778286847806.510260155840317.828421277
847820.333021521840363.230906383847926.445896812840528.325998269
#Sta/Elev= 30
9774.823200.90629782.067198.42469793.722196.94149805.378197.45019828.814201.0585
9853.809201.33159872.307200.49659900.134194.49449911.473193.53599922.763190.2902
9932.198189.34449944.496189.20669954.825186.23869974.927176.92959995.042170.7646
 10005.1170.785110025.26176.910610035.26179.182410045.26180.893910055.41 181.323
10086.86185.784910120.45192.218910132.05192.770510155.65192.052210167.57190.8289
10203.73184.902510215.78186.084210235.77192.312710251.94 195.102 10292.1198.7117
#Mann= 3 , 0 , 0
9774.823    0.04       09774.823    0.04       0 10292.1    0.04       0
#XS Ineff= 2 , 0
       0                               0
Bank Sta=9774.823,10292.1
Exp/Cntr=0.3,0.1

Type RM Length L Ch R = 1 ,9214.958,299.027800,299.027800,299.027800
XS GIS Cut Line= 6
847650.693211982840110.336530841847661.847231042840175.856108887
847667.957466139840265.804826772847665.112276601840336.349482575
847655.597319696840395.914421059847713.982355511840619.060051493
#Sta/Elev= 30
9666.625195.23499681.601197.25859701.928197.98969722.142198.23569742.296197.7628
9772.421196.24389812.481 195.5059832.491192.20799852.491191.99579882.561190.1097
9892.597188.19819923.193176.7079  9933.4174.10279943.528172.8317 9963.61171.8919
9973.752172.49289984.075171.36949994.397168.128510004.77169.601310025.48178.0163
10035.83180.372210066.88182.805410087.59183.257210108.29187.597110118.64191.4978
   10129197.155710139.41 200.45910149.81203.606110170.63208.448210185.26211.1425
#Mann= 3 , 0 , 0
9666.625    0.04       09666.625    0.04       010185.26    0.04       0
#XS Ineff= 2 , 0
       0                               0
Bank Sta=9666.625,10185.26
Exp/Cntr=0.3,0.1

Type RM Length L Ch R = 1 , 8915.93,149.513900,149.513900,149.513900
XS GIS Cut Line= 6
847493.970678112840151.355793982847523.082696095 840316.09476826
 847488.92699211840380.391100507847467.846678523840436.929083639
847459.502071662840495.312517487847460.286544647840575.878980587
#Sta/Elev= 30
9873.628190.62039897.689190.96789918.043191.57439928.219191.34289938.396190.5538
 9958.75189.46599969.017186.56949979.285179.19979989.552 169.3039999.813164.8033
   10010  168.5210020.19170.263610030.32170.854310041.44171.131610062.05 172.953
10073.59175.711210085.13 177.79110119.48179.640510141.38179.3124 10162.4180.7457
10203.42187.339410223.54189.2673 10243.6190.2376 10263.6 192.042 10273.6193.3139
10283.61194.300910293.62195.648510303.63196.440210313.65197.521410314.53197.3719
#Mann= 3 , 0 , 0
9873.628    0.06       09873.628    0.06       010314.53    0.06       0
#XS Ineff= 2 , 0
       0                               0
Bank Sta=9873.628,10314.53
Exp/Cntr=0.3,0.1

Type RM Length L Ch R = 1 ,8766.416,149.513800,149.513800,149.513800
XS GIS Cut Line= 6
847306.620026519840168.196301984847331.478820493 840229.22047318
847409.011557381840394.344642787847422.512089887840431.800449907
847431.438771936840476.120125267847442.748391108840580.587209727
#Sta/Elev= 30
9817.915187.3525 9836.06186.81999846.858185.92499857.655184.62719868.453183.0707
9890.244177.95449901.379176.43149912.514 175.4259937.282172.04559945.919171.2649
9979.303169.42799990.221167.2828    9999164.617710001.12164.222610012.09165.9762
10023.07168.450110034.05169.663310045.02170.226210083.92 175.45610109.34180.0186
10118.67181.097610139.94 184.29710150.14186.284410160.21186.986210184.37189.8171
10210.51194.672210230.62196.002210240.68196.147310250.74197.031710256.36197.2196
#Mann= 3 , 0 , 0
9817.915  0.0443       09817.915  0.0443       010256.36  0.0443       0
#XS Ineff= 2 , 0
       0                               0
Bank Sta=9817.915,10256.36
Exp/Cntr=0.3,0.1

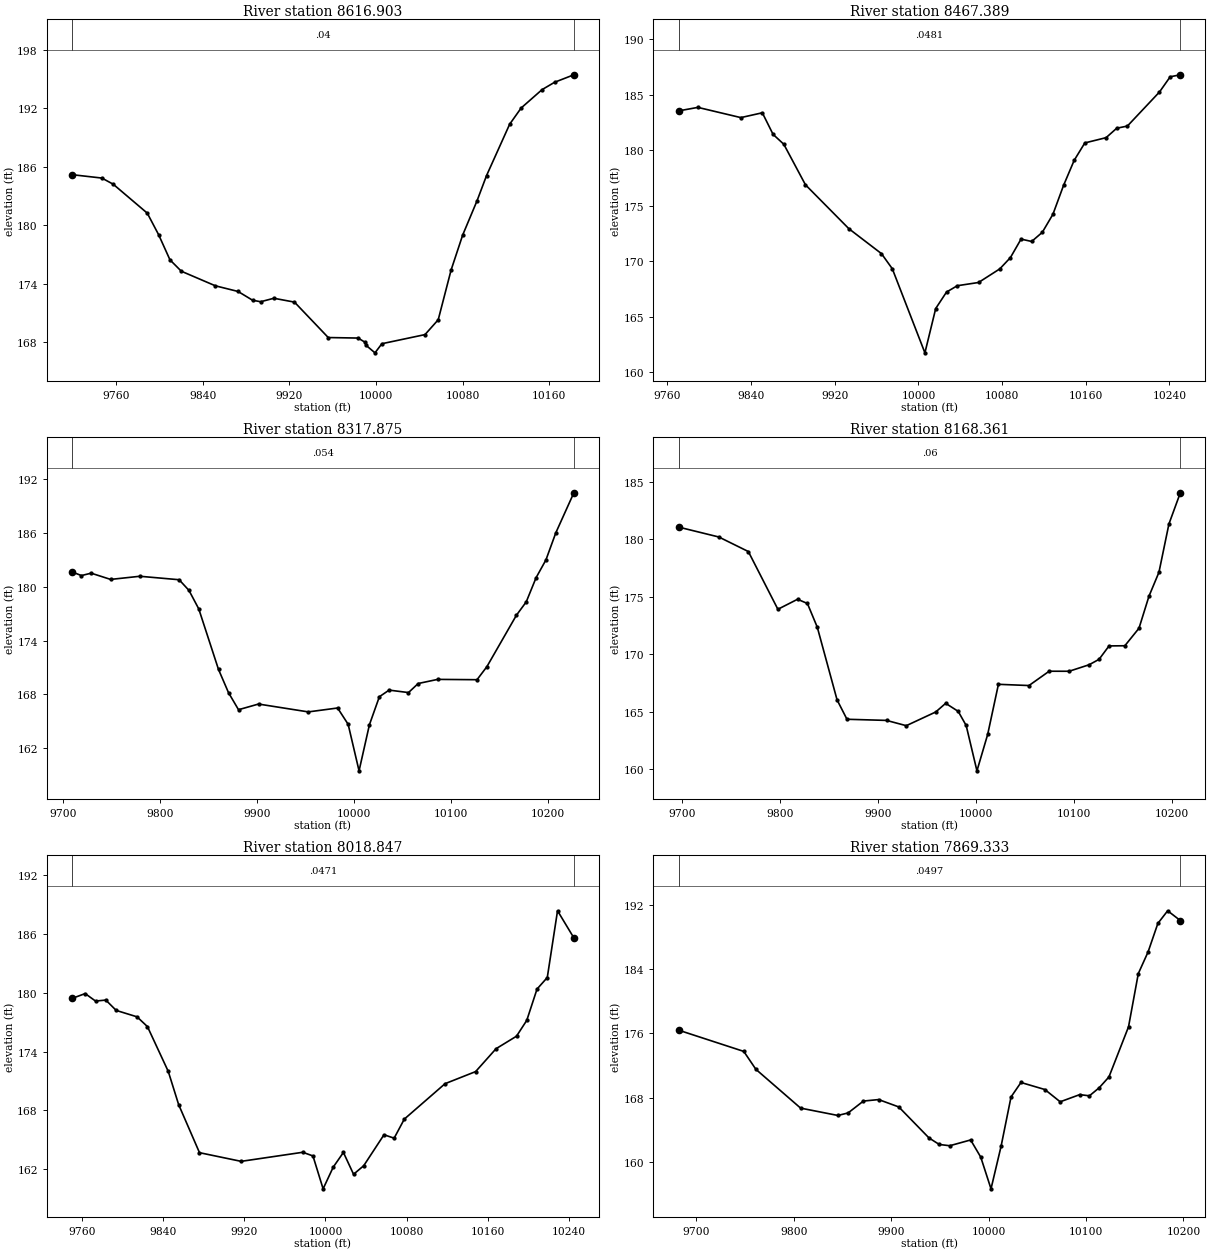
Type RM Length L Ch R = 1 ,8616.903,149.513900,149.513900,149.513900
XS GIS Cut Line= 6
847189.200143618840178.750898195847261.591981136840414.401649391
847270.552318099840429.759249897847318.110512731840482.456186926
847350.125338414840554.498444068847362.244153087840602.199085713
#Sta/Elev= 30
9719.068185.20939746.602184.86229757.092184.2307 9788.56181.26479799.049179.0547
9809.539 176.4749820.028175.30699851.496 173.8119872.475173.22999885.944 172.327
9893.393172.17769905.565172.53319924.609172.13749955.825 168.5049983.388168.4514
9989.564168.0385 9990.94167.6913    9999166.9352 10005.4167.870910045.24168.8059
10057.46170.328710069.37175.433110080.07179.018710093.36182.539110102.14185.1228
10123.47190.382110134.11192.049710153.39193.929510165.06194.690510182.81195.4556
#Mann= 3 , 0 , 0
9719.068    0.04       09719.068    0.04       010182.81    0.04       0
#XS Ineff= 2 , 0
       0                               0
Bank Sta=9719.068,10182.81
Exp/Cntr=0.3,0.1

Type RM Length L Ch R = 1 ,8467.389,149.513900,149.513900,149.513900
XS GIS Cut Line= 6
847098.716802856840186.884232193 847101.11803885840199.834723746
847122.638545141840290.981685889847164.381534481840442.420244592
847192.315533081 840595.88783877 847204.95262911840654.473675175
#Sta/Elev= 30
9770.554183.55429789.033183.87149830.133182.95029850.683183.38499860.958  181.44
9871.233180.5469 9891.93176.8925 9933.45172.9351 9964.59170.6897 9974.97169.3272
10006.16161.745810016.49165.742110026.82167.223810037.11167.795110057.44168.0871
10077.76169.313610087.93170.330310098.09171.997410108.26171.785310118.42172.6094
10128.59174.236810138.75176.840710148.91179.099310159.08180.666910179.41181.1421
10189.57181.9908 10199.8182.189310230.49185.260310240.72  186.6310250.41186.8105
#Mann= 3 , 0 , 0
9770.554  0.0481       09770.554  0.0481       010250.41  0.0481       0
#XS Ineff= 2 , 0
       0                               0
Bank Sta=9770.554,10250.41
Exp/Cntr=0.3,0.1

Type RM Length L Ch R = 1 ,8317.875,149.513900,149.513900,149.513900
XS GIS Cut Line= 6
847005.186552405840195.402734755847025.213104381840340.010571569
847050.835126747840447.649252022847033.657534101840506.804707859
847032.813262489840533.101612298847061.545905448840703.246713855
#Sta/Elev= 30
9708.878181.67359718.528181.26379728.583181.53099748.693 180.8349778.858 181.185
9819.422180.79929829.568179.61399839.714177.54549860.097170.79439870.425168.2045
9880.753166.3026 9901.41166.9345 9952.82166.05879983.083166.49399993.977164.6741
10005.23159.485410015.95164.629910026.21167.750310036.26168.489310056.28168.2149
10066.32 169.22510086.41169.684910127.05169.648710137.22171.098710167.72 176.836
10177.89178.331710188.05181.028810198.22183.010710208.39186.026110227.05190.4968
#Mann= 3 , 0 , 0
9708.878   0.054       09708.878   0.054       010227.05   0.054       0
#XS Ineff= 2 , 0
       0                               0
Bank Sta=9708.878,10227.05
Exp/Cntr=0.3,0.1

Type RM Length L Ch R = 1 ,8168.361,149.513900,149.513900,149.513900
XS GIS Cut Line= 6
846911.993140456840204.000936453846887.094743742840468.284209028
 846890.72429247840487.554360042846907.807958626840525.863416772
846919.322513187840567.926009684846945.512090075840706.419027349
#Sta/Elev= 30
9696.643181.04579737.725180.18459767.827178.91929797.954173.90039818.039174.7719
9828.081174.40319838.155172.33679858.318166.0231  9868.4164.33979908.727164.2408
 9928.89163.78169958.944164.97459969.064165.72629981.839165.02559989.962   163.8
10000.95159.8566 10011.9 163.02410022.85167.3781   10054167.2713 10074.6168.5161
10094.95168.512810115.31 169.07610125.49169.550510135.66170.715710151.77170.7295
 10166.2172.252810176.37175.036210186.55 177.11710196.73181.316310208.35184.0276
#Mann= 3 , 0 , 0
9696.643    0.06       09696.643    0.06       010208.35    0.06       0
#XS Ineff= 2 , 0
       09897.929                       0
Bank Sta=9696.643,10208.35
Exp/Cntr=0.3,0.1

Type RM Length L Ch R = 1 ,8018.847,149.513900,149.513900,149.513900
XS GIS Cut Line= 6
846822.156462362840212.289439492846784.068532086840384.850838141
846776.662747553840443.545035648846777.569947945840533.065497917
846786.313447762840627.167038363 846797.18837464840700.910594013
#Sta/Elev= 30
9750.312179.42019763.239179.91169773.409179.1508 9783.58 179.2499793.805178.1966
9814.329177.5435 9824.59176.54699845.114171.98069855.375168.58969875.899 163.699
9916.946162.81529977.691163.74049987.721163.36539997.725160.014210007.73162.2324
10017.73163.722410027.73161.498210037.73162.368510057.73165.525210067.73165.1772
10077.74167.118910117.91170.730110148.04171.962710168.13174.291610188.33175.5694
10198.44177.181310208.55180.372310218.66181.547810228.76188.349710244.85185.5884
#Mann= 3 , 0 , 0
9750.312  0.0471       09750.312  0.0471       010244.85  0.0471       0
#XS Ineff= 2 , 0
       09948.905                       0
Bank Sta=9750.312,10244.85
Exp/Cntr=0.3,0.1

Type RM Length L Ch R = 1 ,7869.333,149.513800,149.513800,149.513800
XS GIS Cut Line= 6
846751.535736708840218.805042157846663.701098954840501.733874611
846650.422451186840552.792950009846645.347836904840603.858090658
  846645.9025668840637.734597098846653.452485756840717.945958634
#Sta/Elev= 30
9681.773176.38669748.757173.73939761.176171.51079807.094166.68279845.328165.7688
9855.847166.08449871.562167.56229887.185167.74579907.874 166.8299938.909162.9694
9949.426162.1587  9960.2162.00299981.616162.72149991.985160.587710002.53156.6382
10012.85161.922310023.09168.071610033.29169.8733 10057.8168.996910073.55167.4699
10093.57168.360310103.57168.214310113.57169.2142 10123.6170.562210143.69 176.799
10153.73183.421710163.78186.121110173.82189.667810183.87191.239410196.87190.0248
#Mann= 3 , 0 , 0
9681.773  0.0497       09681.773  0.0497       010196.87  0.0497       0
#XS Ineff= 2 , 0
       0 9885.41                       0
Bank Sta=9681.773,10196.87
Exp/Cntr=0.3,0.1

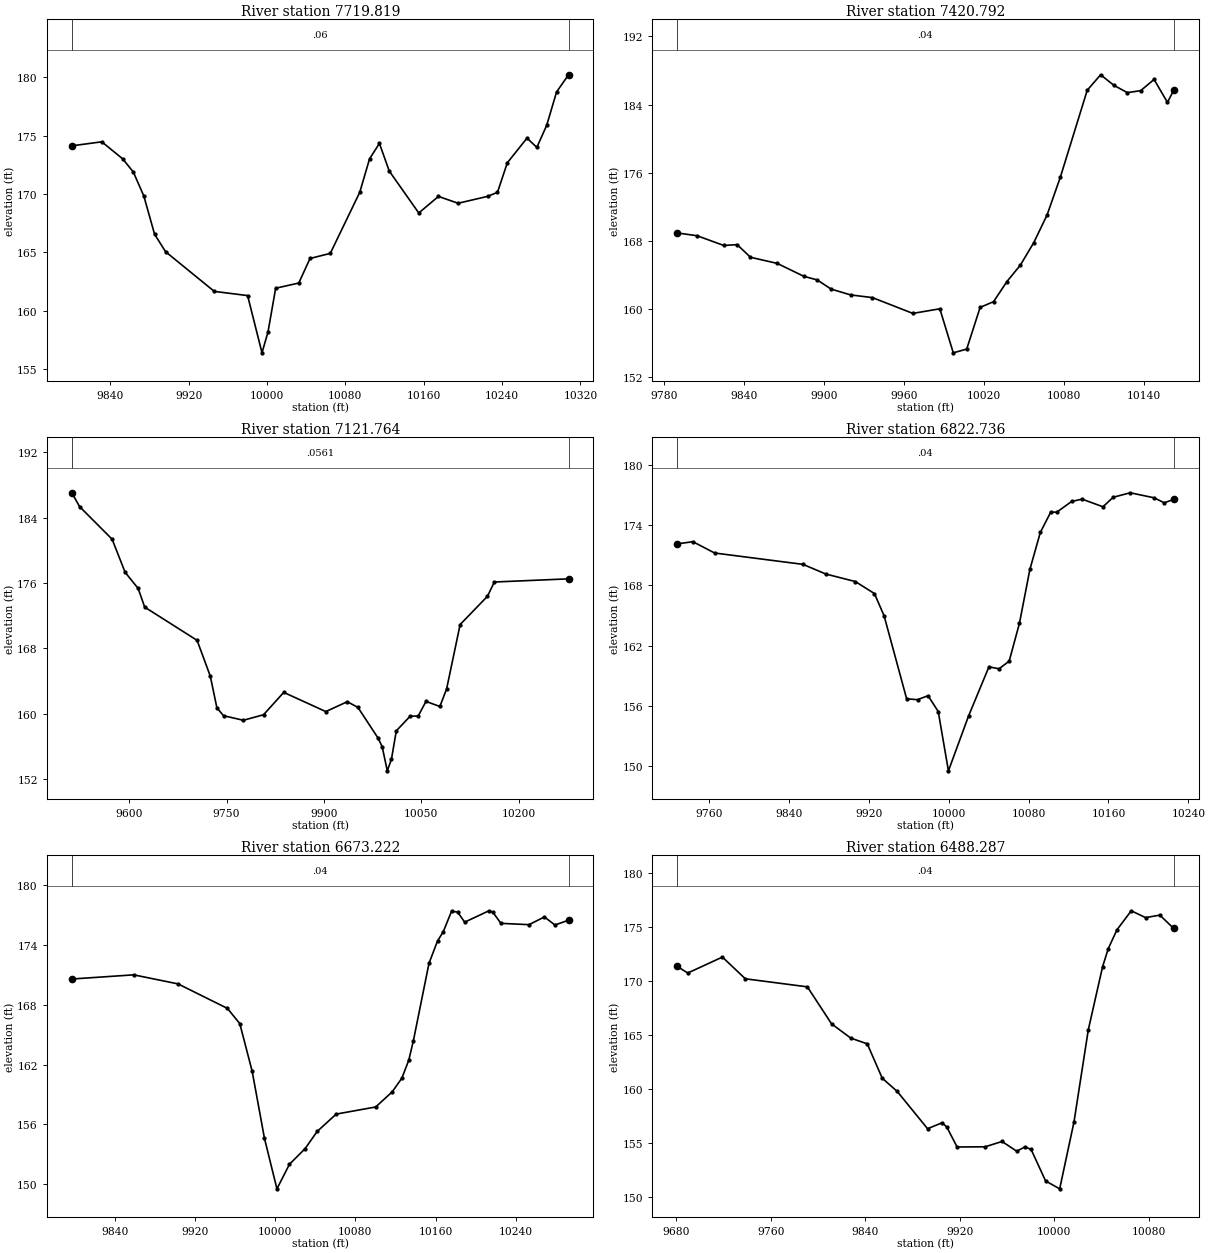
Type RM Length L Ch R = 1 ,7719.819,299.027800,299.027800,299.027800
XS GIS Cut Line= 6
846674.289553863840225.931922122846625.909218426840342.142223595
846599.839841281 840380.39184911846564.045531909 840419.53538107
846550.848914764840450.658264202846574.155875726840697.164524966
#Sta/Elev= 30
9800.627174.11579831.241174.46039852.725172.98989863.468171.8671 9874.21169.8092
9885.107 166.5559896.317165.05319946.113 161.6519980.144161.29349994.841156.3897
   10001158.187210008.79161.920810032.42162.3669 10043.9164.471510064.58164.9051
10094.65170.1309 10104.7173.003710114.75174.3242 10124.8 171.95710154.94168.3641
10175.04169.784310195.13169.197310225.28169.788710235.33170.132110245.37172.6616
10265.47174.776710275.53173.9804 10285.6175.877610295.67  178.7310307.92180.1998
#Mann= 3 , 0 , 0
9800.627    0.06       09800.627    0.06       010307.92    0.06       0
#XS Ineff= 2 , 0
       0                               0
Bank Sta=9800.627,10307.92
Exp/Cntr=0.3,0.1

Type RM Length L Ch R = 1 ,7420.792,299.027800,299.027800,299.027800
XS GIS Cut Line= 6
846409.575348507840329.826940778846409.575348507840436.156315005
846416.999104432840458.850359094846413.361570788840488.379600539
846426.337017879840589.407141128846434.020370182840699.653482375
#Sta/Elev= 30
9789.889168.95289805.062 168.6179825.062167.47449835.062167.57639845.062166.0909
9865.062165.37599885.062163.85849895.062163.43439905.523162.35989920.096161.6781
9936.534161.35939966.791159.50779987.034160.04749997.112154.881710007.18155.3221
10017.24160.2133 10027.3160.884610037.36163.248210047.42165.171710057.46167.8084
10067.48171.0682 10077.5175.539510097.55185.687110107.58187.4995 10117.6186.2558
10127.63185.404310137.65185.638810147.67186.9533 10157.7184.257110162.36185.6746
#Mann= 3 , 0 , 0
9789.889    0.04       09789.889    0.04       010162.36    0.04       0
#XS Ineff= 2 , 0
       0                               0
Bank Sta=9789.889,10162.36
Exp/Cntr=0.3,0.1

Type RM Length L Ch R = 1 ,7121.764,299.027700,299.027700,299.027700
XS GIS Cut Line= 6
 846425.78035701839873.089732182846408.012744858840052.488305864
846373.945725632840201.168005624846334.365573135840284.939051095
846256.790459636840372.763168703846202.424199743840586.949274236
#Sta/Elev= 30
 9511.49187.02919523.433  185.349573.572181.35469593.628 177.3089613.726175.3341
9623.805173.04919704.557168.9874 9724.91164.60929735.086160.73769745.263159.7747
 9775.84159.21719806.964159.89239838.089 162.6269902.926160.27979936.063161.4848
 9952.46160.7875 9983.66157.01659989.791155.98769997.719 153.03410004.13 154.472
10011.59157.924610032.92159.711210045.38159.7409 10057.3161.5229 10078.7160.9001
10089.12163.049410109.95170.921210152.12174.379710162.68176.119910277.07176.5072
#Mann= 3 , 0 , 0
 9511.49  0.0561       0 9511.49  0.0561       010277.07  0.0561       0
#XS Ineff= 2 , 0
       09945.159                       0
Bank Sta=9511.49,10277.07
Exp/Cntr=0.3,0.1

Type RM Length L Ch R = 1 ,6822.736,149.513900,149.513900,149.513900
XS GIS Cut Line= 6
846017.065113114840129.979166547 846062.99297374840234.315033945
846126.589969236840349.580281853846142.797810527840440.484392186
 846168.48495981840525.239198052846182.818493383840594.301414119
#Sta/Elev= 30
9727.954172.11169743.982172.33229765.675171.20689854.212170.07729877.044169.1154
9906.614168.36719925.758167.17049935.451164.94319957.966156.70639968.862156.6142
9979.389157.01129989.604155.43969999.814149.536710020.09155.022810040.37 159.881
10050.51159.689410060.64160.448910070.92164.215510081.37169.575210091.82173.2491
10102.27175.276810108.27175.267910123.17176.333110133.62176.567510154.52175.8064
10164.82176.753510181.82177.198610205.75176.6996 10215.9176.199410225.34 176.538
#Mann= 3 , 0 , 0
9727.954    0.04       09727.954    0.04       010225.34    0.04       0
#XS Ineff= 2 , 0
       0                               0
Bank Sta=9727.954,10225.34
Exp/Cntr=0.3,0.1

Type RM Length L Ch R = 1 ,6673.222,184.935600,184.935600,184.935600
XS GIS Cut Line= 6
845872.778680518 840216.08558599846004.064077122840406.455534445
 846094.07677086840467.773903554846125.812212149 840500.14652776
846148.385277719840533.072184816846172.996846107840597.984531847
#Sta/Elev= 30
9797.232170.57359858.993170.99179903.154170.08529952.447167.62899964.771166.1046
9977.094161.34149989.417154.591110001.82149.545410014.33  152.0110029.89  153.57
10041.92155.294510060.96157.036110100.32157.749810116.81159.267310126.46160.6413
 10133.3162.433410137.88164.366810153.48172.1389   10162174.382910167.76175.3178
   10176 177.36810182.05177.279810189.09176.271610213.34 177.41210217.14177.2749
10225.26176.152710253.19176.019910268.63176.793110279.11175.985710292.71176.4671
#Mann= 3 , 0 , 0
9797.232    0.04       09797.232    0.04       010292.71    0.04       0
#XS Ineff= 2 , 0
       0                               0
Bank Sta=9797.232,10292.71
Exp/Cntr=0.3,0.1

Type RM Length L Ch R = 1 ,6488.287,131.292200,131.292200,131.292200
XS GIS Cut Line= 4
845778.739961147840322.609300226 845848.16847679840397.099088207
845991.168589026840508.575628117846104.643538803840586.302002817
#Sta/Elev= 30
9680.454171.39199689.636170.75629718.969172.23669738.403170.22049790.945169.4733
9811.399166.04169827.664164.71539841.663  164.189854.343 160.9919867.022159.7638
9892.724156.30369905.061156.85419908.989156.4583 9917.74154.60649941.519154.6236
9955.779155.11879968.244154.21219974.969154.60529980.365 154.3929992.664151.4547
10004.61150.720410016.73  156.9310028.85165.490610040.97171.353210045.75173.0204
10053.09174.763310065.21 176.53510077.33175.901310089.45176.131810101.14174.8978
#Mann= 3 , 0 , 0
9680.454    0.04       09680.454    0.04       010101.14    0.04       0
#XS Ineff= 2 , 0
       0                               0
Bank Sta=9680.454,10101.14
Exp/Cntr=0.3,0.1