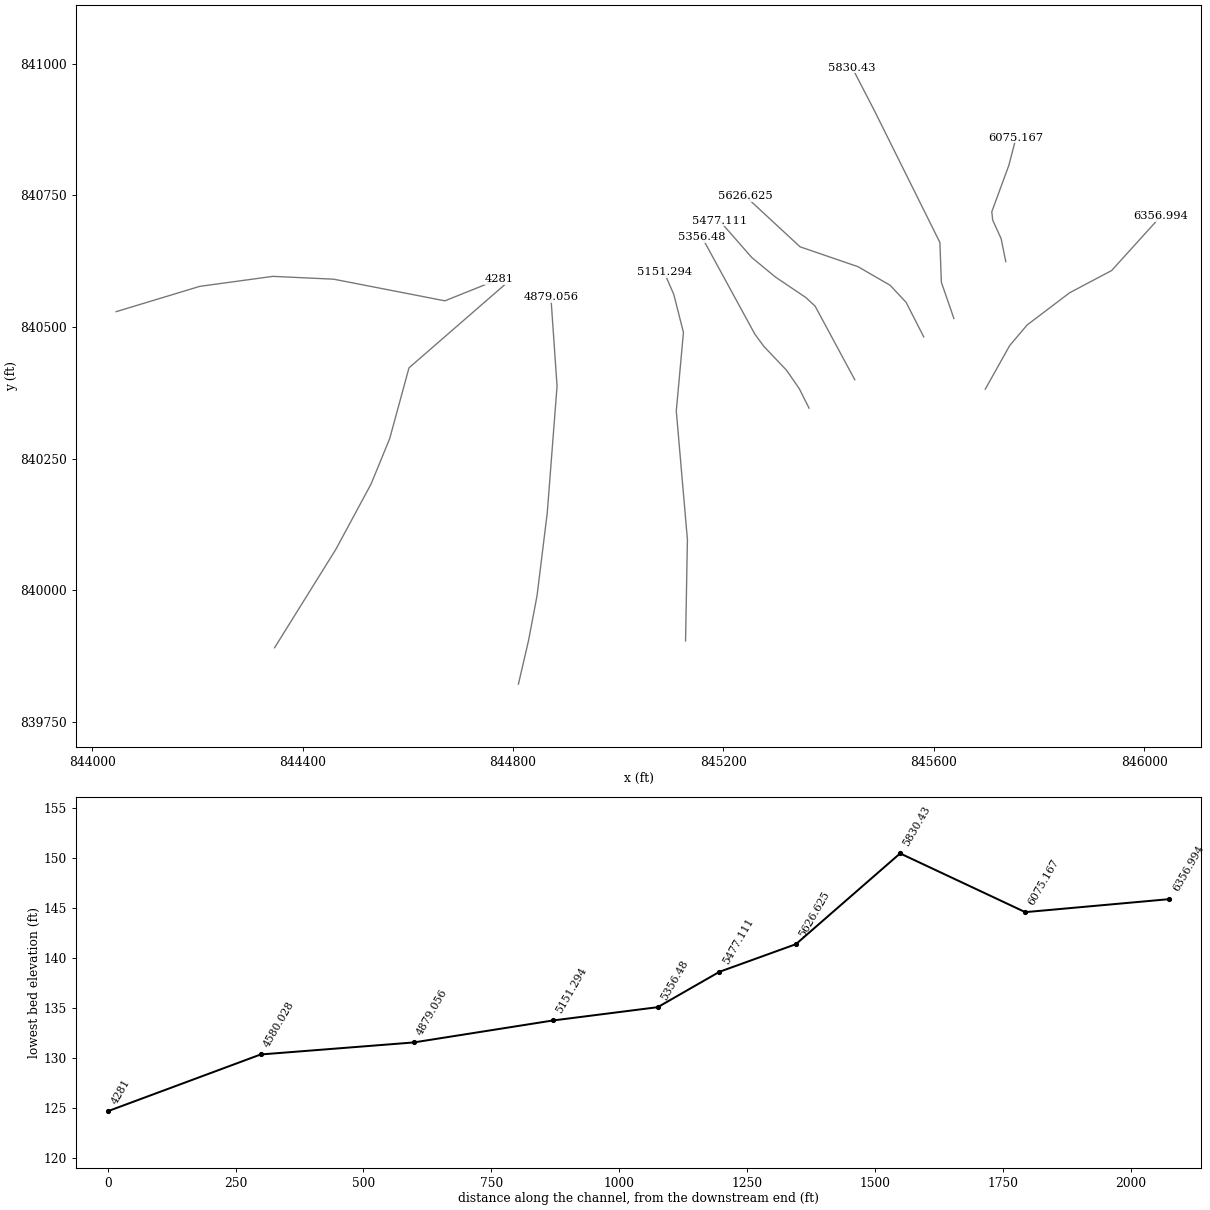
HEC-RAS study 18599_ras.prj: 18599

--- 18599_ras.g01 (geometry) --- (continued)

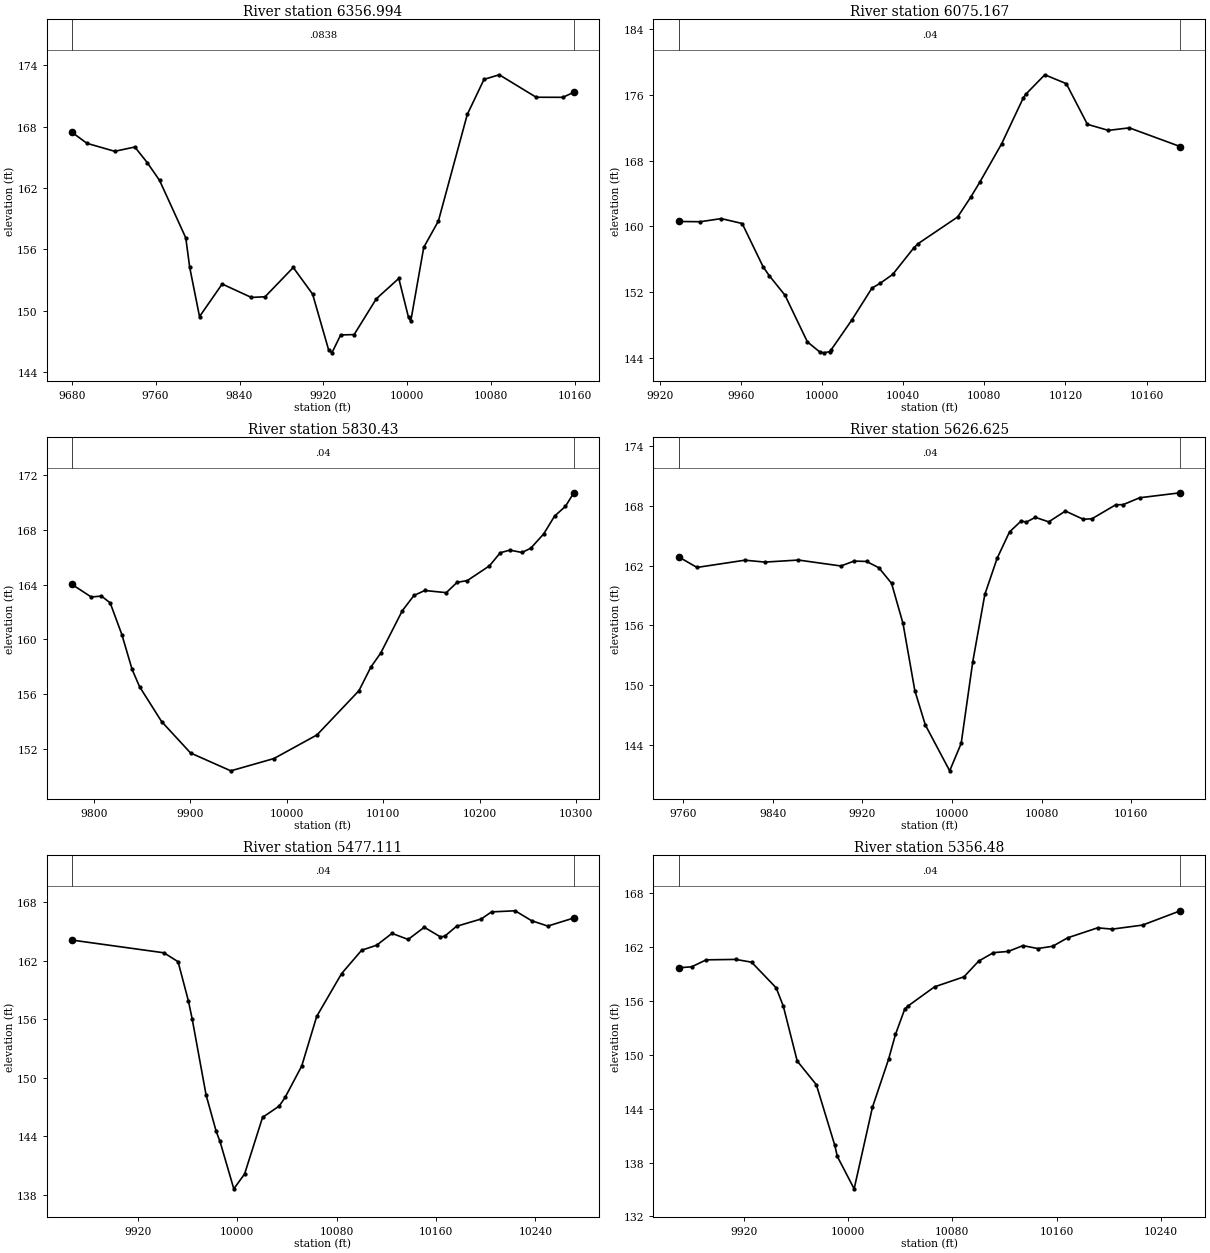
Type RM Length L Ch R = 1 ,6356.994,281.827700,281.827700,281.827700
XS GIS Cut Line= 6
845697.553498625840382.092450958845743.844548007840464.642435095
845777.061152941 840503.91865352845857.723586063840565.027267872
845937.683223043840607.294815301846031.505527397840710.790891995
#Sta/Elev= 30
9680.369167.45229694.537166.37689721.053165.59659740.197166.01549752.011164.4951
9763.826162.74129788.783157.12399792.493 154.252 9801.88149.42049823.465152.6095
9851.295151.29479864.377151.36159891.229154.22559909.672151.62449924.923146.1749
9928.114145.8729 9936.42147.62389949.279147.65959970.456151.16689991.852153.1539
10001.13149.331710003.27148.979910015.64156.195410029.58158.763610057.17169.2071
10073.13172.636910087.65173.085210122.84 170.88610148.26170.879310158.76171.3726
#Mann= 3 , 0 , 0
9680.369  0.0838       09680.369  0.0838       010158.76  0.0838       0
#XS Ineff= 2 , 0
       09942.394                       0
Bank Sta=9680.369,10158.76
Exp/Cntr=0.3,0.1

Type RM Length L Ch R = 1 ,6075.167,244.736200,244.736200,244.736200
XS GIS Cut Line= 6
845736.501602839840624.252267075845727.694077755840667.910543407
845711.626690032840703.188501425845709.947717854  840718.9223976
845742.401837854840807.222523082845755.944629037840859.346111283
#Sta/Elev= 30
 9929.26160.58169940.026160.55439950.314160.93419960.632160.33599970.951155.0575
9973.954153.98649981.753151.58959992.753145.9162    9999144.6502   10001144.5721
10003.79144.7322 10004.3144.872810014.55148.5292 10024.6152.463210028.55 153.036
10034.83154.129310045.16 157.34810047.41 157.89210066.84161.132410073.31163.5555
10077.68165.342110088.52170.051110099.19175.642910100.43 176.09210109.79178.4635
10120.39177.381910130.79172.426210141.12171.686810151.45171.9941 10176.6169.7107
#Mann= 3 , 0 , 0
 9929.26    0.04       0 9929.26    0.04       0 10176.6    0.04       0
#XS Ineff= 2 , 0
       0                               0
Bank Sta=9929.26,10176.6
Exp/Cntr=0.3,0.1

Type RM Length L Ch R = 1 , 5830.43,203.805500,203.805500,203.805500
XS GIS Cut Line= 5
845637.943016112840516.226849243845614.117463917840584.900499746
845611.314457774840660.581665576 845487.98218751840908.647709161
845444.535592288840992.737893432
#Sta/Elev= 30
9777.469164.0036 9797.34163.09289807.925163.16049816.957162.66399829.094160.3559
9839.679157.82589847.466156.56079870.272154.02849900.292151.74069941.994 150.442
9986.665 151.33510031.34153.056510074.85156.276210087.17157.991910097.31159.0026
10119.77162.093510131.85163.202410143.01163.565510165.35163.407910176.52 164.158
10187.16164.288410210.08165.359510221.33166.313310231.21166.503610243.84166.3314
10252.99166.647510266.35167.686410277.61168.982610288.87  169.6910297.58170.6766
#Mann= 3 , 0 , 0
9777.469    0.04       09777.469    0.04       010297.58    0.04       0
#XS Ineff= 2 , 0
       0 9945.88                       0
Bank Sta=9777.469,10297.58
Exp/Cntr=0.3,0.1

Type RM Length L Ch R = 1 ,5626.625,149.513900,149.513900,149.513900
XS GIS Cut Line= 6
845580.584470714840481.345679812845547.193740125840546.761539521
845516.754253817840579.330816262845455.522465557840614.702362369
845345.579697315840652.360275266845241.815256673840748.369919248
#Sta/Elev= 30
9755.703162.8756 9772.18161.80829814.988162.5353 9832.85162.34399862.763162.5503
9900.774 161.9539912.477162.44569923.627162.4095 9934.64 161.7779945.987160.2118
9956.213156.17779966.796149.4228 9976.13145.99019997.911141.371110008.19144.1323
10018.55152.347610029.32159.096910040.34162.737510051.35165.373210061.72166.4694
10066.53166.368410074.39166.841910086.36166.388810101.29 167.47210117.23166.6469
10125.08166.701910146.16168.097810152.95168.118910167.63168.809110203.94169.3086
#Mann= 3 , 0 , 0
9755.703    0.04       09755.703    0.04       010203.94    0.04       0
#XS Ineff= 2 , 0
       0                               0
Bank Sta=9755.703,10203.94
Exp/Cntr=0.3,0.1

Type RM Length L Ch R = 1 ,5477.111,120.631000,120.631000,120.631000
XS GIS Cut Line= 6
 845449.51549904840399.967691904845374.152383233 840539.70264233
 845356.74554021840555.918934553845298.516124354840595.118912161
845253.591623652840632.230430681845192.663501402840701.778151215
#Sta/Elev= 30
9867.227164.11649941.093162.81449952.511161.9004 9960.81157.88619963.929155.9934
9975.073148.22329983.178144.50649986.216143.4812 9997.36138.610110006.02140.1294
10020.49145.936810033.88147.096910038.62147.9836   10052151.202510064.06156.2904
10084.07160.678710100.22163.078110112.28163.590910124.65164.805410137.63164.1825
 10150.6165.432210163.57164.449410167.01164.506910176.54  165.53 10196.4166.2818
 10204.7167.0059 10223.7167.122110236.97166.1036   10250165.553710270.96166.3857
#Mann= 3 , 0 , 0
9867.227    0.04       09867.227    0.04       010270.96    0.04       0
#XS Ineff= 2 , 0
       0                               0
Bank Sta=9867.227,10270.96
Exp/Cntr=0.3,0.1

Type RM Length L Ch R = 1 , 5356.48,205.185800,205.185800,205.185800
XS GIS Cut Line= 6
845362.639720199840346.028334712845343.982169827840383.090651269
845319.905518622840417.852176957 845276.46788014840463.618662089
845259.469985964840486.798219809 845159.34895179840670.198734384
#Sta/Elev= 30
9870.137159.71819880.147159.82269891.357 160.6029913.959160.64859926.123160.3415
9944.974157.48229950.452155.43579961.102149.3192 9975.74146.68789989.866139.9416
9991.866138.681910004.73135.076710018.74144.154710031.14149.530310036.42152.2875
10043.54 155.12310045.77155.430510066.33157.591710088.92158.710510100.22160.4656
10111.51161.403910122.81161.537710134.11162.188510145.41161.8621 10156.9162.1136
10168.38163.057710191.35164.167910202.57 164.026 10225.8164.474510254.74166.0701
#Mann= 3 , 0 , 0
9870.137    0.04       09870.137    0.04       010254.74    0.04       0
#XS Ineff= 2 , 0
       0                               0
Bank Sta=9870.137,10254.74
Exp/Cntr=0.3,0.1

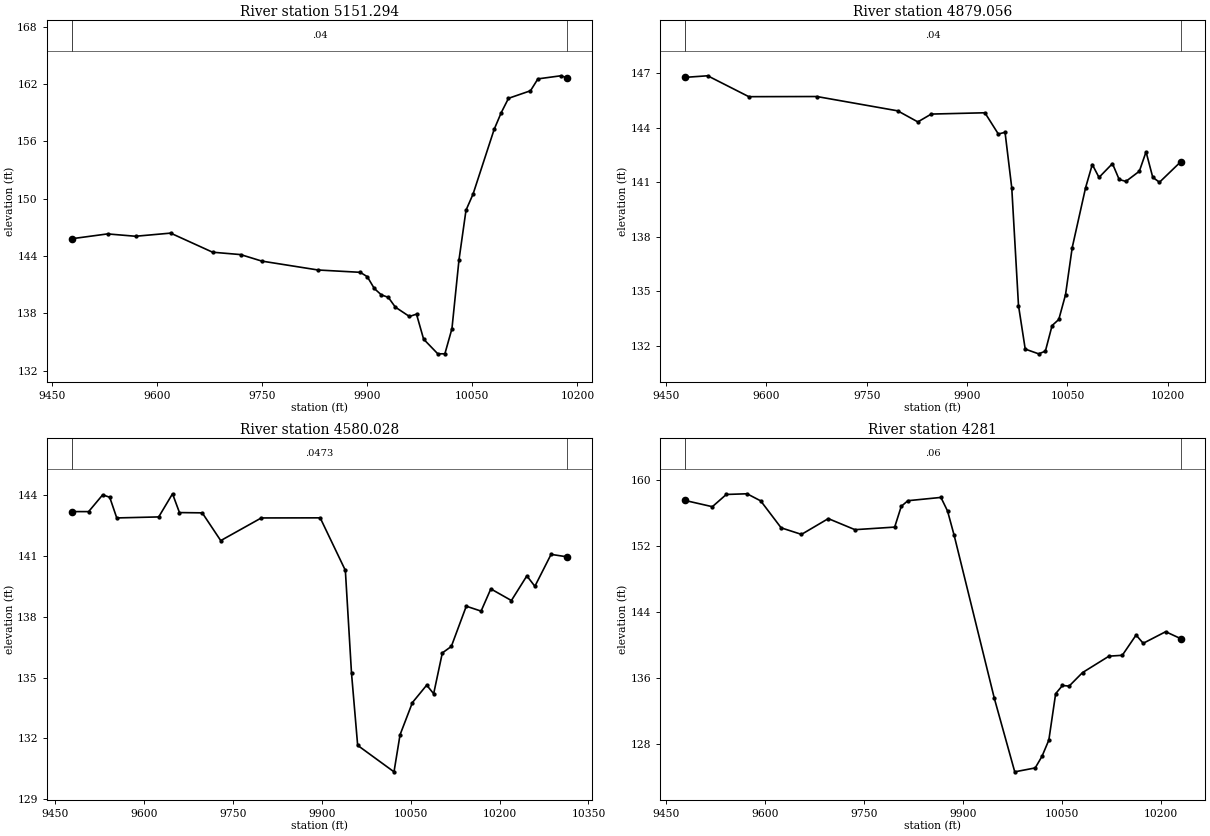
Type RM Length L Ch R = 1 ,5151.294,272.238700,272.238700,272.238700
XS GIS Cut Line= 6
845127.891156974839903.932287587845131.443572249840096.216305879
845110.286957296840340.610992874845123.892747693840489.698384184
845105.606032465840561.846345773845087.332638772840603.647317228
#Sta/Elev= 30
9477.819145.80659528.953146.31219569.002146.06619619.004146.39529679.024144.3937
9719.103144.14419749.226143.46439829.667142.53079889.941142.28699899.956141.8276
9909.972140.59519919.987139.9273    9930139.66349940.014138.64199960.121137.6611
9970.265137.9043 9980.41135.2852 10000.7133.7458 10010.8133.7501 10020.9136.3883
10030.97 143.60310040.97148.796510050.97150.468710081.19157.267110091.33159.0228
10101.66160.519510133.08161.3115 10143.7162.556510176.44162.881110185.88162.6557
#Mann= 3 , 0 , 0
9477.819    0.04       09477.819    0.04       010185.88    0.04       0
#XS Ineff= 2 , 0
       09860.062                       0
Bank Sta=9477.819,10185.88
Exp/Cntr=0.3,0.1

Type RM Length L Ch R = 1 ,4879.056,299.027700,299.027700,299.027700
XS GIS Cut Line= 6
844810.233865045839821.926558165844829.455947601839904.578522027
844845.644704513839989.841127751844865.059789473840147.313074237
844883.664830601840387.940087595844871.975509364840556.523564435
#Sta/Elev= 30
9478.303146.7815 9512.26146.86919573.769145.71789675.379145.72639796.268144.9377
9826.374144.32789846.419144.75959926.598144.83119946.653143.66099956.704 143.754
9966.755140.69049976.806 134.2119986.857 131.81210006.95131.550810016.98131.6988
10027.01133.107410037.04 133.44610047.07134.804410057.08137.402710077.09140.7065
10087.09141.980910097.13141.269110117.22142.031310127.26 141.157 10137.3141.0497
10157.39141.608910167.43142.678110177.47141.274510187.52141.003810219.12142.1264
#Mann= 3 , 0 , 0
9478.303    0.04       09478.303    0.04       010219.12    0.04       0
#XS Ineff= 2 , 0
       0                               0
Bank Sta=9478.303,10219.12
Exp/Cntr=0.3,0.1

Type RM Length L Ch R = 1 ,4580.028,299.027800,299.027800,299.027800
XS GIS Cut Line= 6
844346.792234152839891.022803564844463.207328837840077.825981274
844530.231299589840202.044146228844565.560096324840288.129054865
844602.271044726840422.532146491844784.451253039840580.672383267
#Sta/Elev= 30
9478.326143.19699506.772143.19569530.499144.02499542.363 143.9049554.227142.8838
9625.011142.93369648.299144.07619660.008143.14829698.447143.1344 9729.63141.7643
9798.075142.88329897.407 142.8889939.858140.29499950.242135.22169960.626131.6572
10021.94130.350210032.12132.178310053.01133.7704 10077.1134.630610088.83134.2053
10103.45  136.2210118.65 136.54110143.86138.526710168.84138.284210185.27139.3813
10219.97138.806510246.05140.024110259.58139.509110286.89141.084710314.53140.9606
#Mann= 3 , 0 , 0
9478.326  0.0473       09478.326  0.0473       010314.53  0.0473       0
#XS Ineff= 2 , 0
       0                               0
Bank Sta=9478.326,10314.53
Exp/Cntr=0.3,0.1

Type RM Length L Ch R = 1 ,    4281,0.000000,0.000000,0.000000
XS GIS Cut Line= 6
844045.734403828840529.248683255  844204.8327168 840577.33471959
 844343.62711486840596.272953961844459.130499017840590.904792883
844670.441468408 840549.81682373 844773.91186136840591.211774945
#Sta/Elev= 30
9478.415157.50049519.953156.7429 9541.11158.22399572.543158.3052 9593.22157.4485
9624.236 154.1879655.072153.39319695.718155.30239736.098153.96489796.317154.2757
9806.317156.78789816.317157.4674 9866.43157.86519876.473156.21889886.516153.2662
9947.422133.55419978.328124.678210009.35125.152210019.67 126.561   10030128.5204
10040.32134.128710050.64135.120110060.77135.048110081.03 136.67910121.17138.6669
10141.33138.772110162.26141.223710173.03140.222610207.07141.625310229.77140.7922
#Mann= 3 , 0 , 0
9478.415    0.06       09478.415    0.06       010229.77    0.06       0
#XS Ineff= 2 , 0
       0                               0
Bank Sta=9478.415,10229.77
Exp/Cntr=0.3,0.1